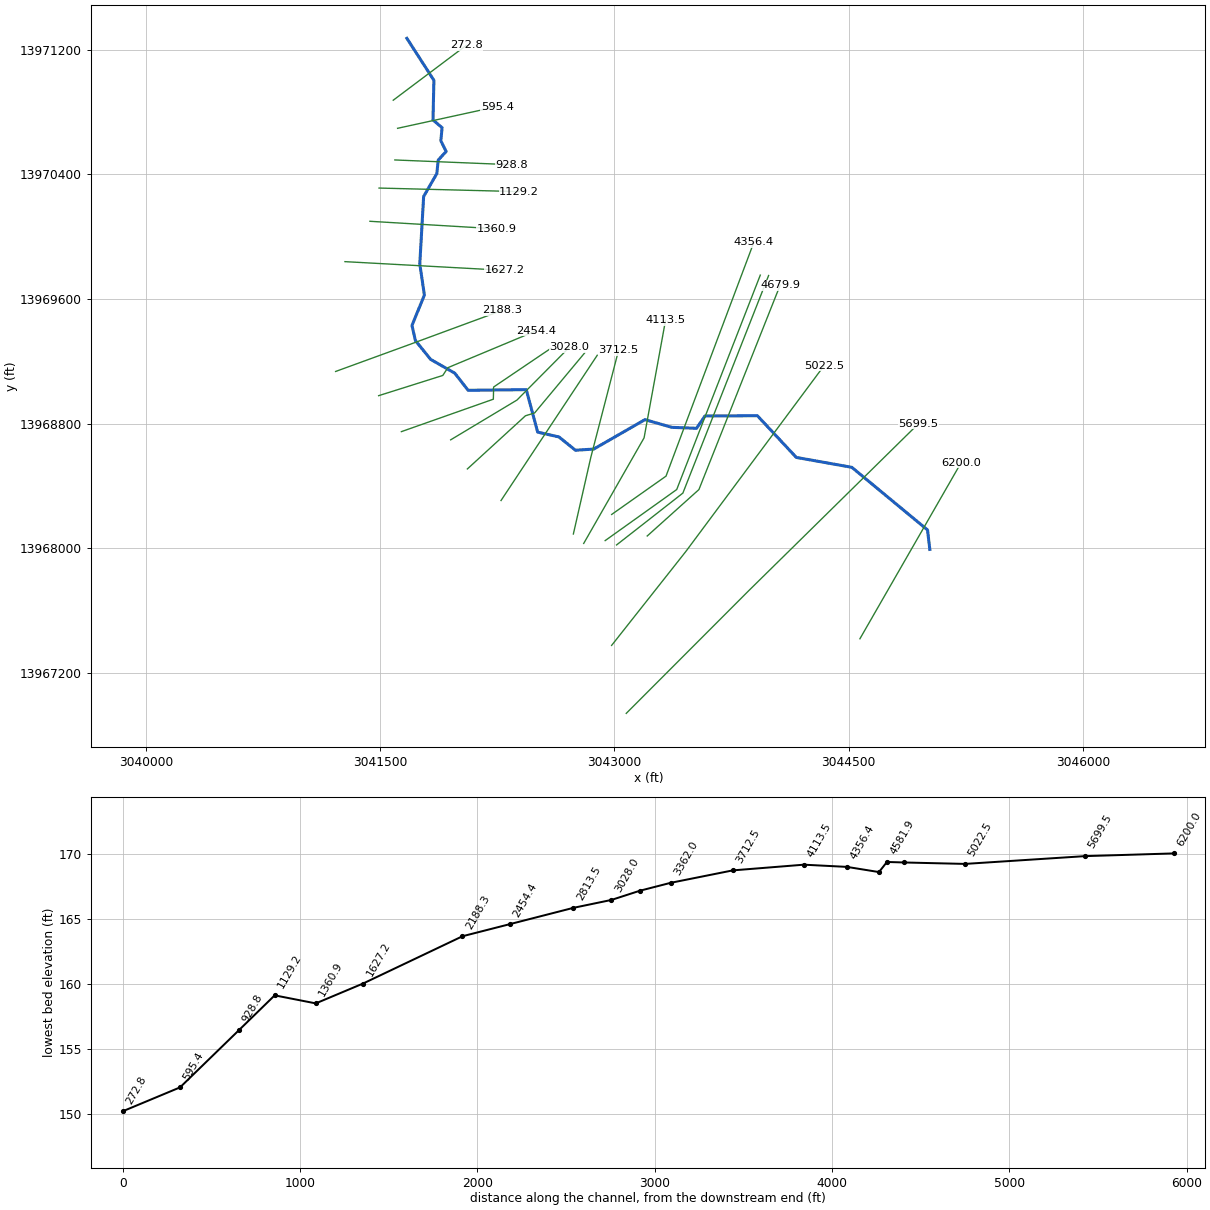
--- J131-01-00.PRJ (project) ---

Proj Title=J131-01-00
Current Plan=p02
Default Exp/Contr=.3,.1
English Units
Geom File=g01
Flow File=f02
Flow File=f03
Plan File=p02
Plan File=p03
Y Axis Title=Elevation
X Axis Title(PF)=Main Channel Distance
X Axis Title(XS)=Station
BEGIN DESCRIPTION:
Spring Creek
Tributary 1.25 to Boggs Gully
HCFCD Unit J131-01-00
Flood Hazard Model
10, 2, 1, 0.2% Event
Filename J131-01-00.prj
Prepared by: Halff Associates, Inc.     Date: 03/24/2004
Reviewed by:                  Date:
STATUS Final RAS
END DESCRIPTION:
DSS File=dss
DSS Export Rating Curves= 0
DSS Export Rating Curve Sorted= 0
DSS Export Volume Flow Curves= 0
DXF OffsetX= 0
DXF OffsetY= 0
DXF ScaleX= 1
DXF ScaleY= 10

--- J131-01-00.p02 (plan) ---

Plan Title=FEMA Effective June 2007
Version=Version 3.0.1  Mar 2001
Short Identifier=FEMAeff0607
Geom File=g01
Flow File=f02
Subcritical Flow
K Sum by GR= 0
Std Step Tol= 0.01
Critical Tol= 0.01
Num of Std Step Trials= 20
Max Error Tol= 0.3
Flow Tol Ratio= 0.001
Split Flow NTrial= 30
Split Flow Tol= 0.02
Split Flow Ratio= 0.02
Log Output Level= 0
Friction Slope Method= 1
Unsteady Friction Slope Method= 2
Parabolic Critical Depth
Global Vel Dist= 0 , 0 , 0
Global Log Level= 0
CheckData=True
Encroach Param=-1 ,0,0, 0
Computation Interval=1HOUR
Output Interval=1HOUR
Run HTab= 0
Run UNet= 0
Run PostProcess= 0
UNET Theta= 1
UNET ZTol= 0.02
UNET ZSATol= 0.1
UNET MxIter= 20
UNET MaxInSteps= 20
UNET DtIC= 0
UNET DtMin= 0
UNET MaxCRTS= 20
UNET WFStab= 2
UNET SFStab= 1
UNET WFX= 1
UNET SFX= 1
UNET Convert EG Bridges=-1
UNET Use Existing IB Tables=-1
Instantaneous Interval=1HOUR
Write IC File= 0
Write Velocity= 0
Write Detailed= 0

--- J131-01-00.p03 (plan) ---

Plan Title=Floodway
Version=Version 3.0.1  Mar 2001
Short Identifier=Floodway0607
Geom File=g01
Flow File=f03
Subcritical Flow
K Sum by GR= 0
Std Step Tol= 0.01
Critical Tol= 0.01
Num of Std Step Trials= 20
Max Error Tol= 0.3
Flow Tol Ratio= 0.001
Split Flow NTrial= 30
Split Flow Tol= 0.02
Split Flow Ratio= 0.02
Log Output Level= 0
Friction Slope Method= 1
Unsteady Friction Slope Method= 2
Parabolic Critical Depth
Global Vel Dist= 0 , 0 , 0
Global Log Level= 0
CheckData=True
Encroach Param=-1 ,0,0, 7
Encroach River=J131-01-00
Encroach Reach=Reach - 1
Encroach Node=6200.0
       1  4972.5  5055.5       0       0       0       0       0       0
       0       0       0       0       0       0       0       0       0
Encroach Node=5699.5
       1    4840  5007.3       0       0       0       0       0       0
       0       0       0       0       0       0       0       0       0
Encroach Node=5022.5
       1    4905  5007.3       0       0       0       0       0       0
       0       0       0       0       0       0       0       0       0
Encroach Node=4679.9
       1  4987.9    5100       0       0       0       0       0       0
       0       0       0       0       0       0       0       0       0
Encroach Node=4581.9
       1  4987.9    5160       0       0       0       0       0       0
       0       0       0       0       0       0       0       0       0
Encroach Node=4559.4
       1  4987.9    5160       0       0       0       0       0       0
       0       0       0       0       0       0       0       0       0
Encroach Node=4536.9
       1  4987.9    5160       0       0       0       0       0       0
       0       0       0       0       0       0       0       0       0
Encroach Node=4356.4
       1    4990    5205       0       0       0       0       0       0
       0       0       0       0       0       0       0       0       0
Encroach Node=4113.5
       1    4980    5100       0       0       0       0       0       0
       0       0       0       0       0       0       0       0       0
Encroach Node=3712.5
       1  4991.1    5180       0       0       0       0       0       0
       0       0       0       0       0       0       0       0       0
Encroach Node=3362.0
       1    4980    5055       0       0       0       0       0       0
       0       0       0       0       0       0       0       0       0
Encroach Node=3188.4
       1    4970    5040       0       0       0       0       0       0
       0       0       0       0       0       0       0       0       0
Encroach Node=3028.0
       1    4955    5030       0       0       0       0       0       0
       0       0       0       0       0       0       0       0       0
Encroach Node=2813.5
       1    4965  5021.1       0       0       0       0       0       0
       0       0       0       0       0       0       0       0       0
Encroach Node=2454.4
       1    4940  5021.1       0       0       0       0       0       0
       0       0       0       0       0       0       0       0       0
Encroach Node=2188.3
       1    4940  5021.1       0       0       0       0       0       0
       0       0       0       0       0       0       0       0       0
Encroach Node=1627.2
       1  4975.7    5032       4      .7               4      .8
       4      .9               4       1               4     1.1
Encroach Node=1360.9
       1  4952.7  5045.8       4      .7               4      .8
       4      .9               4       1               4     1.1
Encroach Node=1129.2
       1    4964  5018.9       4      .7               4      .8
       4      .9               4       1               4     1.1
Encroach Node=928.8
       1    4968    5023       4      .7               4      .8
       4      .9               4       1               4     1.1
Encroach Node=595.4
       1  4945.4  5006.4       4      .7               4      .8
       4      .9               4       1               4     1.1
Encroach Node=272.8
       1  4987.5    5015       4      .7               4      .8
       4      .9               4       1               4     1.1
Encroach Reach=J131-01-00_0003
Encroach Node=6200.0
       1  4972.5  5055.5       0       0       0       0       0       0
       0       0       0       0       0       0       0       0       0
Encroach Node=5699.5
       1    4840  5007.3       0       0       0       0       0       0
       0       0       0       0       0       0       0       0       0
Encroach Node=5022.5
       1    4905  5007.3       0       0       0       0       0       0
       0       0       0       0       0       0       0       0       0
Encroach Node=4679.9
       1  4987.9    5100       0       0       0       0       0       0
       0       0       0       0       0       0       0       0       0
Encroach Node=4581.9
       1  4987.9    5160       0       0       0       0       0       0
       0       0       0       0       0       0       0       0       0
Encroach Node=4559.4
       1  4987.9    5160       0       0       0       0       0       0
       0       0       0       0       0       0       0       0       0
Encroach Node=4536.9
       1  4987.9    5160       0       0       0       0       0       0
       0       0       0       0       0       0       0       0       0
Encroach Node=4356.4
       1    4990    5205       0       0       0       0       0       0
       0       0       0       0       0       0       0       0       0
Encroach Node=4113.5
       1    4980    5100       0       0       0       0       0       0
       0       0       0       0       0       0       0       0       0
Encroach Node=3712.5
       1  4991.1    5180       0       0       0       0       0       0
       0       0       0       0       0       0       0       0       0
Encroach Node=3362.0
       1    4980    5055       0       0       0       0       0       0
       0       0       0       0       0       0       0       0       0
Encroach Node=3188.4
       1    4970    5040       0       0       0       0       0       0
       0       0       0       0       0       0       0       0       0
Encroach Node=3028.0
       1    4955    5030       0       0       0       0       0       0
       0       0       0       0       0       0       0       0       0
Encroach Node=2813.5
       1    4965  5021.1       0       0       0       0       0       0
       0       0       0       0       0       0       0       0       0
Encroach Node=2454.4
       1    4940  5021.1       0       0       0       0       0       0
       0       0       0       0       0       0       0       0       0
Encroach Node=2188.3
       1    4940  5021.1       0       0       0       0       0       0
       0       0       0       0       0       0       0       0       0
Encroach Node=1627.2
       1  4975.7    5032       0       0       0       0       0       0
       0       0       0       0       0       0       0       0       0
Encroach Node=1360.9
       1  4952.7  5045.8       0       0       0       0       0       0
       0       0       0       0       0       0       0       0       0
Encroach Node=1129.2
       1    4964  5018.9       0       0       0       0       0       0
       0       0       0       0       0       0       0       0       0
Encroach Node=928.8
       1    4968    5023       0       0       0       0       0       0
       0       0       0       0       0       0       0       0       0
Encroach Node=595.4
       1  4945.4  5006.4       0       0       0       0       0       0
       0       0       0       0       0       0       0       0       0
Encroach Node=272.8
       1  4987.5    5015       0       0       0       0       0       0
       0       0       0       0       0       0       0       0       0
Computation Interval=1HOUR
Output Interval=1HOUR
Run HTab= 0
Run UNet= 0
Run PostProcess= 0
UNET Theta= 1
UNET ZTol= 0.02
UNET ZSATol= 0.1
UNET MxIter= 20
UNET MaxInSteps= 20
UNET DtIC= 0
UNET DtMin= 0
UNET MaxCRTS= 20
UNET WFStab= 2
UNET SFStab= 1
UNET WFX= 1
UNET SFX= 1
UNET Convert EG Bridges=-1
UNET Use Existing IB Tables=-1
Instantaneous Interval=1HOUR
Write IC File= 0
Write Velocity= 0
Write Detailed= 0

--- J131-01-00.f02 (steady flow) ---

Flow Title=FEMA Effective June 2007
Version=Version 3.0.1  Mar 2001
Number of Profiles= 4
Profile Names=10PCT_10yr, 2PCT_50yr, 1PCT_100yr, 0.2PCT_500yr
River Rch & RM=J131-01-00,J131-01-00_0003,6200.0
      80     130     150     230
River Rch & RM=J131-01-00,J131-01-00_0003,5699.5
     100     160     190     290
River Rch & RM=J131-01-00,J131-01-00_0003,5022.5
     110     170     210     320
River Rch & RM=J131-01-00,J131-01-00_0003,4679.9
     120     190     230     360
River Rch & RM=J131-01-00,J131-01-00_0003,4356.4
     130     200     250     380
River Rch & RM=J131-01-00,J131-01-00_0003,4113.5
     150     230     280     430
River Rch & RM=J131-01-00,J131-01-00_0003,3712.5
     160     250     310     480
River Rch & RM=J131-01-00,J131-01-00_0003,3362.0
     170     270     330     510
River Rch & RM=J131-01-00,J131-01-00_0003,3188.4
     180     280     340     540
River Rch & RM=J131-01-00,J131-01-00_0003,3028.0
     190     300     370     570
River Rch & RM=J131-01-00,J131-01-00_0003,2813.5
     210     330     410     640
River Rch & RM=J131-01-00,J131-01-00_0003,2454.4
     230     360     440     700
River Rch & RM=J131-01-00,J131-01-00_0003,2188.3
     270     420     520     820
River Rch & RM=J131-01-00,J131-01-00_0003,1627.2
     290     450     570     890
River Rch & RM=J131-01-00,J131-01-00_0003,1360.9
     310     480     610     960
River Rch & RM=J131-01-00,J131-01-00_0003,1129.2
     330     510     650    1020
River Rch & RM=J131-01-00,J131-01-00_0003,928.8
     360     560     720    1130
River Rch & RM=J131-01-00,J131-01-00_0003,595.4
     400     620     790    1250
Boundary for River Rch & Prof#=J131-01-00,J131-01-00_0003, 1
Up Type= 0
Dn Type= 3
Dn Slope=.005
Boundary for River Rch & Prof#=J131-01-00,J131-01-00_0003, 2
Up Type= 0
Dn Type= 3
Dn Slope=.005
Boundary for River Rch & Prof#=J131-01-00,J131-01-00_0003, 3
Up Type= 0
Dn Type= 3
Dn Slope=.005
Boundary for River Rch & Prof#=J131-01-00,J131-01-00_0003, 4
Up Type= 0
Dn Type= 3
Dn Slope=.005
DSS Import GetInterval= 0
DSS Import GetPeak= 0
DSS Import FillOption= 0

--- J131-01-00.f03 (steady flow) ---

Flow Title=Floodway
Version=Version 3.0.1  Mar 2001
Number of Profiles= 2
Profile Names=1PCT_100yr, 1PCTFloodway_100yrFW
River Rch & RM=J131-01-00,J131-01-00_0003,6200.0
     150     150
River Rch & RM=J131-01-00,J131-01-00_0003,5699.5
     190     190
River Rch & RM=J131-01-00,J131-01-00_0003,5022.5
     210     210
River Rch & RM=J131-01-00,J131-01-00_0003,4679.9
     230     230
River Rch & RM=J131-01-00,J131-01-00_0003,4356.4
     250     250
River Rch & RM=J131-01-00,J131-01-00_0003,4113.5
     280     280
River Rch & RM=J131-01-00,J131-01-00_0003,3712.5
     310     310
River Rch & RM=J131-01-00,J131-01-00_0003,3362.0
     330     330
River Rch & RM=J131-01-00,J131-01-00_0003,3188.4
     340     340
River Rch & RM=J131-01-00,J131-01-00_0003,3028.0
     370     370
River Rch & RM=J131-01-00,J131-01-00_0003,2813.5
     410     410
River Rch & RM=J131-01-00,J131-01-00_0003,2454.4
     440     440
River Rch & RM=J131-01-00,J131-01-00_0003,2188.3
     520     520
River Rch & RM=J131-01-00,J131-01-00_0003,1627.2
     570     570
River Rch & RM=J131-01-00,J131-01-00_0003,1360.9
     610     610
River Rch & RM=J131-01-00,J131-01-00_0003,1129.2
     650     650
River Rch & RM=J131-01-00,J131-01-00_0003,928.8
     720     720
River Rch & RM=J131-01-00,J131-01-00_0003,595.4
     790     790
Boundary for River Rch & Prof#=J131-01-00,J131-01-00_0003, 1
Up Type= 0
Dn Type= 3
Dn Slope=.005
Boundary for River Rch & Prof#=J131-01-00,J131-01-00_0003, 2
Up Type= 0
Dn Type= 1
Dn Known WS=158.12
DSS Import GetInterval= 0
DSS Import GetPeak= 0
DSS Import FillOption= 0

--- J131-01-00.g01 (geometry) ---

Geom Title=J131-01-00 June 2007
Version=Version 3.0.1  Mar 2001

River Reach=J131-01-00      ,J131-01-00_0003
Reach XY= 30
    3045020.2434   13967992.8899    3045005.6002   13968117.7425
    3044520.6955   13968519.8463    3044165.2497   13968583.1853
    3043916.0506   13968850.8369    3043580.1131   13968849.1007
    3043526.7115   13968770.1913    3043368.5839   13968776.2211
    3043196.0888   13968825.6757    3042868.1838    13968636.909
    3042751.2379   13968629.2328     3042645.362   13968714.6667
    3042508.9887    13968745.555    3042436.1414   13969018.1448
     3042063.747    13969013.977    3041978.1605   13969123.9337
    3041823.4185   13969212.5879    3041726.1001   13969333.1549
    3041704.1164   13969430.2493    3041783.6491   13969624.8913
    3041754.1965   13969825.1694    3041778.7747   13970257.5692
    3041862.9757     13970404.27    3041872.5245   13970491.9444
    3041922.8715   13970546.6311    3041889.0175   13970615.2084
    3041896.8296   13970699.4093    3041838.6705    13970748.888
    3041844.6186   13971003.0965    3041671.5379    13971272.688

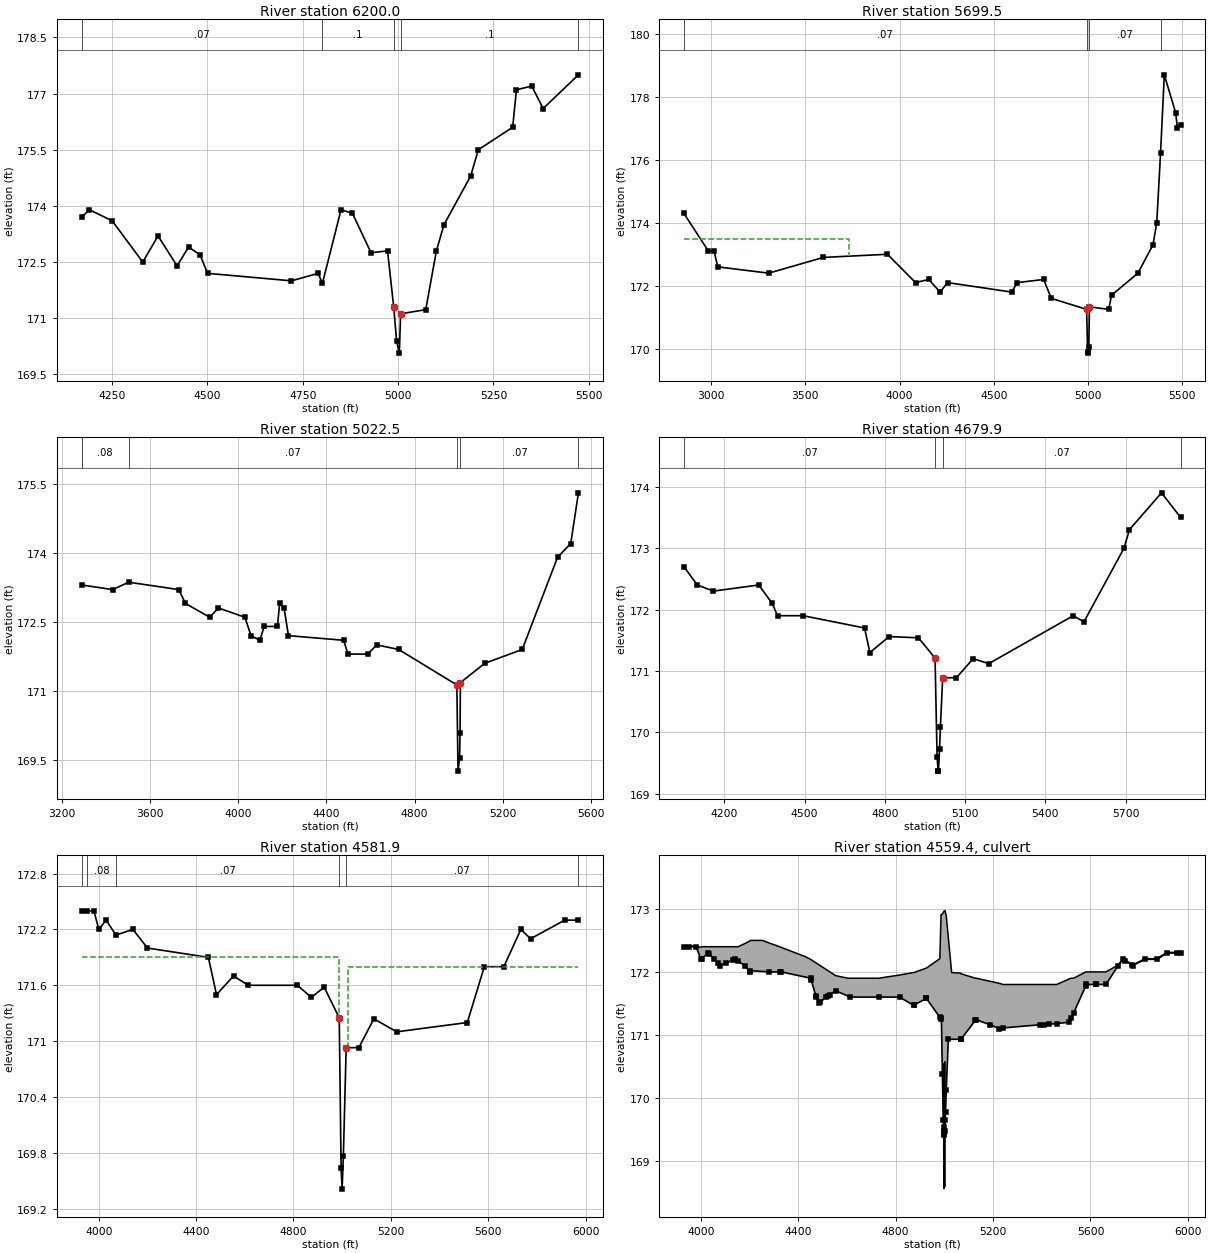
Type RM Length L Ch R = 1 ,6200.0  ,687.75,500.5,487.56
BEGIN DESCRIPTION:
Cross Section XS20
END DESCRIPTION:
XS GIS Cut Line= 2
    3044572.5567    13967419.344    3045220.5093   13968549.2713
#Sta/Elev= 30
  4170.3   173.7  4190.3   173.9  4250.3   173.6  4330.3   172.5  4370.3   173.2
  4420.3   172.4  4450.3   172.9  4480.3   172.7  4500.3   172.2  4720.3     172
  4790.3   172.2  4801.4  171.93  4850.3   173.9  4880.3   173.8  4928.9  172.75
  4972.2   172.8  4988.5  171.29    4996  170.39  5003.1  170.07  5006.5  171.12
  5072.4  171.23  5100.3   172.8  5120.3   173.5  5190.3   174.8  5210.3   175.5
  5300.3   176.1  5310.3   177.1  5350.3   177.2  5380.3   176.6  5472.8   177.5
#Mann= 5 ,-1 , 0
  4170.3     .07       0  4801.4      .1       0  4988.5     .07       0
  5006.5      .1       0  5472.8      .2       0
Bank Sta=4988.5,5006.5
XS Rating Curve= 0
Exp/Cntr=.3,.1

Type RM Length L Ch R = 1 ,5699.5  ,543.38,677,659.57
BEGIN DESCRIPTION:
Cross Section XS19
END DESCRIPTION:
XS GIS Cut Line= 3
    3043076.3656   13966940.7167    3043859.1527    13967726.521
    3044946.0072   13968798.2383
#Sta/Elev= 30
  2855.3   174.3  2985.3   173.1  3015.3   173.1  3035.3   172.6  3305.3   172.4
  3595.3   172.9  3935.3     173  4084.4   172.1  4154.4   172.2  4214.4   171.8
  4254.4   172.1  4594.4   171.8  4624.4   172.1  4764.4   172.2  4804.4   171.6
  4992.2  171.25  4997.5  169.91  5000.7  169.86  5003.7  170.05  5007.3  171.33
  5109.7  171.25  5124.4   171.7  5264.4   172.4  5344.4   173.3  5364.4     174
  5384.5  176.21  5404.4   178.7  5464.4   177.5  5474.4     177  5490.8   177.1
#Mann= 4 ,-1 , 0
  2855.3     .07       0  4992.2     .07       0  5007.3     .07       0
  5384.5      .2       0
#XS Ineff= 2 , 0
       0    3730   173.5               0
Permanent Ineff=
       F       F
Bank Sta=4992.2,5007.3
XS Rating Curve= 0
Exp/Cntr=.3,.1

Type RM Length L Ch R = 1 ,5022.5  ,194.67,342.6,357.63
BEGIN DESCRIPTION:
Cross Section XS18
END DESCRIPTION:
XS GIS Cut Line= 3
    3042982.6385   13967376.9344    3043457.7531   13967979.4135
     3044342.741   13969171.6888
#Sta/Elev= 30
  3290.4   173.3  3430.4   173.2  3503.4  173.36  3730.4   173.2  3760.4   172.9
  3870.4   172.6  3910.4   172.8  4030.4   172.6  4057.7   172.2  4097.7   172.1
  4117.7   172.4  4177.7   172.4  4187.7   172.9  4207.7   172.8  4227.7   172.2
  4477.7   172.1  4497.7   171.8  4587.7   171.8  4627.7     172  4727.7   171.9
  4991.2  171.13  4996.6  169.26  5003.6  169.54  5005.7  170.09  5007.3  171.18
  5117.7   171.6  5287.7   171.9  5447.7   173.9  5507.7   174.2  5542.5   175.3
#Mann= 6 , 1 , 0
  3290.4      .2       0  3290.4     .08       0  3503.4     .07       0
  4991.2     .07       0  5007.3     .07       0  5542.5      .2       0
Bank Sta=4991.2,5007.3
XS Rating Curve= 0
Exp/Cntr=.3,.1

Type RM Length L Ch R = 1 ,4679.9  ,82.44,98,85.96
BEGIN DESCRIPTION:
Cross Section XS17
END DESCRIPTION:
XS GIS Cut Line= 3
    3043210.5822   13968079.0134    3043541.5778   13968376.9095
    3044061.8551   13969688.7742
#Sta/Elev= 27
  4049.1   172.7  4099.1   172.4  4159.1   172.3  4329.1   172.4  4379.1   172.1
  4399.1   171.9  4494.4   171.9  4724.4   171.7  4744.4   171.3  4815.9  171.56
    4926  171.54  4987.9  171.21  4995.5   169.6  4999.7  169.37  5000.6  169.38
  5004.8  169.73  5007.9  170.09  5016.4  170.89  5067.8  170.89  5130.2   171.2
  5188.8  171.12  5504.4   171.9  5544.4   171.8  5694.4     173  5714.4   173.3
  5834.4   173.9  5905.7   173.5
#Mann= 4 ,-1 , 0
  4049.1     .07       0  4987.9     .07       0  5016.4     .07       0
  5905.7      .2       0
Bank Sta=4987.9,5016.4
XS Rating Curve= 0
Exp/Cntr=.5,.3

Type RM Length L Ch R = 1 ,4581.9  ,45,45,45
BEGIN DESCRIPTION:
Upstream Section of Bridge/Culvert/Weir
END DESCRIPTION:
XS GIS Cut Line= 3
    3043014.2471     13968021.55    3043438.8899   13968354.2925
    3043987.9025   13969750.6252
#Sta/Elev= 30
  3930.4   172.4  3953.1   172.4  3980.4   172.4  4000.4   172.2  4030.4   172.3
  4070.9  172.14  4140.4   172.2  4200.4     172  4450.4   171.9  4483.8   171.5
  4553.8   171.7  4613.8   171.6  4815.9   171.6  4873.6  171.47    4926  171.58
  4987.9  171.25  4995.5  169.64  4999.7  169.41  5004.8  169.77  5016.4  170.93
  5068.2  170.93  5130.2  171.24  5223.8   171.1  5513.8   171.2  5583.8   171.8
  5663.8   171.8  5733.8   172.2  5773.8   172.1  5913.8   172.3  5970.2   172.3
#Mann= 6 ,-1 , 0
  3930.4      .2       0  3953.1     .08       0  4070.9     .07       0
  4987.9     .07       0  5016.4     .07       0  5970.2      .2       0
#XS Ineff= 2 , 0
       0 4987.23   171.9 5023.07       0   171.8
Permanent Ineff=
       F       F
Bank Sta=4987.9,5016.4
XS Rating Curve= 0
Exp/Cntr=.5,.3

Type RM Length L Ch R = 2 ,4559.4  ,,,
BEGIN DESCRIPTION:
E. HUFFSMITH ROAD
Structure ID: J131-01-00-01
END DESCRIPTION:
Bridge Culvert--1,0,-1,-1, 0
Deck Dist Width WeirC Skew NumUp NumDn MinLoCord MaxHiCord MaxSubmerge Is_Ogee
10,25,3,0, 73, 73, , , .95, 0, 1,1,,
  3930.4  3953.1  3980.4  4000.4  4003.1  4030.4  4033.1  4053.1  4133.1  4140.4
  4153.1  4180.4  4200.4  4203.1  4250.4  4253.1  4260.4  4280.4  4323.1  4430.4
  4450.4  4553.8  4603.8  4613.8  4730.8  4815.9  4873.6  4875.1  4925.7    4926
  4981.4  4986.5  4987.9    4992  4995.5  4998.1  4999.3  4999.7  5000.2  5000.6
  5000.8    5003  5004.8  5007.9    5030  5067.8  5068.2  5127.4  5130.2  5188.8
  5223.8  5241.2  5391.2  5411.2  5431.2  5461.2  5513.8  5521.2  5531.2  5581.2
  5583.8  5621.2  5623.8  5663.8  5713.8  5733.8  5741.2  5771.2  5773.8  5823.8
  5873.8  5913.8  5953.8
   172.4  172.41  172.41  172.39   172.4   172.4   172.4   172.4   172.4   172.4
   172.4  172.45  172.49   172.5   172.5   172.5  172.49  172.46   172.4  172.24
   172.2  171.94   171.9   171.9   171.9  171.95  171.99  171.99  172.06  172.06
  172.21  172.91  172.91  172.92  172.94  172.96  172.96  172.96  172.96  172.97
  172.97  172.97  172.94  172.89  171.99  171.98  171.97   171.9   171.9  171.85
  171.82   171.8   171.8   171.8   171.8   171.8  171.89   171.9   171.9     172
     172     172     172     172  172.11  172.21  172.19  172.12  172.11  172.21
  172.21  172.31  172.31
                                                                                
                                                                                
                                                                                
                                                                                
                                                                                
                                                                                
                                                                                
                        
  3930.4  3953.1  3980.4  4000.4  4003.1  4030.4  4033.1  4053.1  4133.1  4140.4
  4153.1  4180.4  4200.4  4203.1  4250.4  4253.1  4260.4  4280.4  4323.1  4430.4
  4450.4  4553.8  4603.8  4613.8  4730.8  4815.9  4873.6  4875.1  4925.7    4926
  4981.4  4986.5  4987.9    4992  4995.5  4998.1  4999.3  4999.7  5000.2  5000.6
  5000.8    5003  5004.8  5007.9    5030  5067.8  5068.2  5127.4  5130.2  5188.8
  5223.8  5241.2  5391.2  5411.2  5431.2  5461.2  5513.8  5521.2  5531.2  5581.2
  5583.8  5621.2  5623.8  5663.8  5713.8  5733.8  5741.2  5771.2  5773.8  5823.8
  5873.8  5913.8  5953.8
   172.4  172.41  172.41  172.39   172.4   172.4   172.4   172.4   172.4   172.4
   172.4  172.45  172.49   172.5   172.5   172.5  172.49  172.46   172.4  172.24
   172.2  171.94   171.9   171.9   171.9  171.95  171.99  171.99  172.06  172.06
  172.21  172.91  172.91  172.92  172.94  172.96  172.96  172.96  172.96  172.97
  172.97  172.97  172.94  172.89  171.99  171.98  171.97   171.9   171.9  171.85
  171.82   171.8   171.8   171.8   171.8   171.8  171.89   171.9   171.9     172
     172     172     172     172  172.11  172.21  172.19  172.12  172.11  172.21
  172.21  172.31  172.31
                                                                                
                                                                                
                                                                                
                                                                                
                                                                                
                                                                                
                                                                                
                        
BR Coef= 1 , 0 , 0 ,1.25, 0 ,,,.8,-1,2,1,
WSPro=,,,, 1 ,,,, 0 ,,,, 0 ,,,,-1 ,-1 ,-1 , 0 , 0 , 0 , 0 , 0
Culvert=1,2,,25,.015,.5,1,1,3,168.55,4998.1,168.55,4998.1,Culvert #1  , 0 ,10
Culvert Bottom n=.015
Culvert=1,2,,25,.015,.5,1,1,3,168.58,5001.5,168.58,5001.5,Culvert #2  , 0 ,10
Culvert Bottom n=.015
BR U #Sta/Elev= 81
  3930.4   172.4  3953.1   172.4  3980.4   172.4  4000.4   172.2  4003.1  172.21
  4030.4   172.3  4033.1  172.29  4053.1  172.21  4070.9  172.14  4080.4   172.1
  4103.1  172.14  4133.1  172.19  4140.4   172.2  4153.1  172.17  4180.4   172.1
  4200.4     172  4203.1  172.02  4280.4     172  4323.1     172  4330.4     172
  4450.4   171.9  4453.1  171.87  4473.1  171.61  4473.8   171.6  4483.8   171.5
  4490.8  171.52  4513.8   171.6  4520.8  171.62  4530.8  171.64  4553.8   171.7
  4613.8   171.6  4730.8   171.6  4815.9   171.6  4873.6  171.47  4875.1  171.47
  4925.7  171.58    4926  171.58  4981.4  171.28  4986.5  171.26  4987.9  171.25
    4992  170.38  4995.5  169.64  4998.1  169.53  4999.3  169.48  4999.7  169.41
  5000.2  169.46  5000.6  169.42  5000.8  169.48    5003  169.64  5004.8  169.77
  5007.9  170.13  5016.4  170.93  5067.8  170.93  5068.2  170.93  5127.4  171.23
  5130.2  171.24  5188.8  171.16  5223.8   171.1  5241.2  171.11  5391.2  171.16
  5411.2  171.16  5431.2  171.17  5461.2  171.18  5513.8   171.2  5521.2  171.26
  5531.2  171.35  5581.2  171.78  5583.8   171.8  5621.2   171.8  5623.8   171.8
  5663.8   171.8  5713.8   172.1  5733.8   172.2  5741.2  172.18  5771.2  172.11
  5773.8   172.1  5823.8   172.2  5873.8   172.2  5913.8   172.3  5953.8   172.3
  5970.2   172.3
BR U #Mann= 5
  3930.4      .2  3953.1     .08  4070.9     .07  4987.9     .06  5016.4     .07
BR D #Sta/Elev= 81
  3930.4   172.4  3953.1   172.4  3980.4   172.4  4000.4   172.2  4003.1  172.21
  4030.4   172.3  4033.1  172.29  4053.1  172.21  4070.9  172.14  4080.4   172.1
  4103.1  172.14  4133.1  172.19  4140.4   172.2  4153.1  172.17  4180.4   172.1
  4200.4     172  4203.1  172.02  4280.4     172  4323.1     172  4330.4     172
  4450.4   171.9  4453.1  171.87  4473.1  171.61  4473.8   171.6  4483.8   171.5
  4490.8  171.52  4513.8   171.6  4520.8  171.62  4530.8  171.64  4553.8   171.7
  4613.8   171.6  4730.8   171.6  4815.9   171.6  4873.6  171.47  4875.1  171.47
  4925.7  171.58    4926  171.58  4981.4  171.28  4986.5  171.26  4987.9  171.25
    4992  170.38  4995.5  168.86  4998.1  168.74  4999.3   168.7  4999.7  168.63
  5000.2  168.65  5000.6  168.64  5000.8   168.7    5003  169.64  5004.8  169.77
  5007.9  170.13  5016.4  170.93  5067.8  170.93  5068.2  170.93  5127.4  171.23
  5130.2  171.24  5188.8  171.16  5223.8   171.1  5241.2  171.11  5391.2  171.16
  5411.2  171.16  5431.2  171.17  5461.2  171.18  5513.8   171.2  5521.2  171.26
  5531.2  171.35  5581.2  171.78  5583.8   171.8  5621.2   171.8  5623.8   171.8
  5663.8   171.8  5713.8   172.1  5733.8   172.2  5741.2  172.18  5771.2  172.11
  5773.8   172.1  5823.8   172.2  5873.8   172.2  5913.8   172.3  5953.8   172.3
  5970.2   172.3
BR D #Mann= 5
  3930.4      .2  3953.1     .08  4070.9     .07  4987.9     .06  5016.4     .07
BC Design=,, 0 ,, 0 ,,,,,,

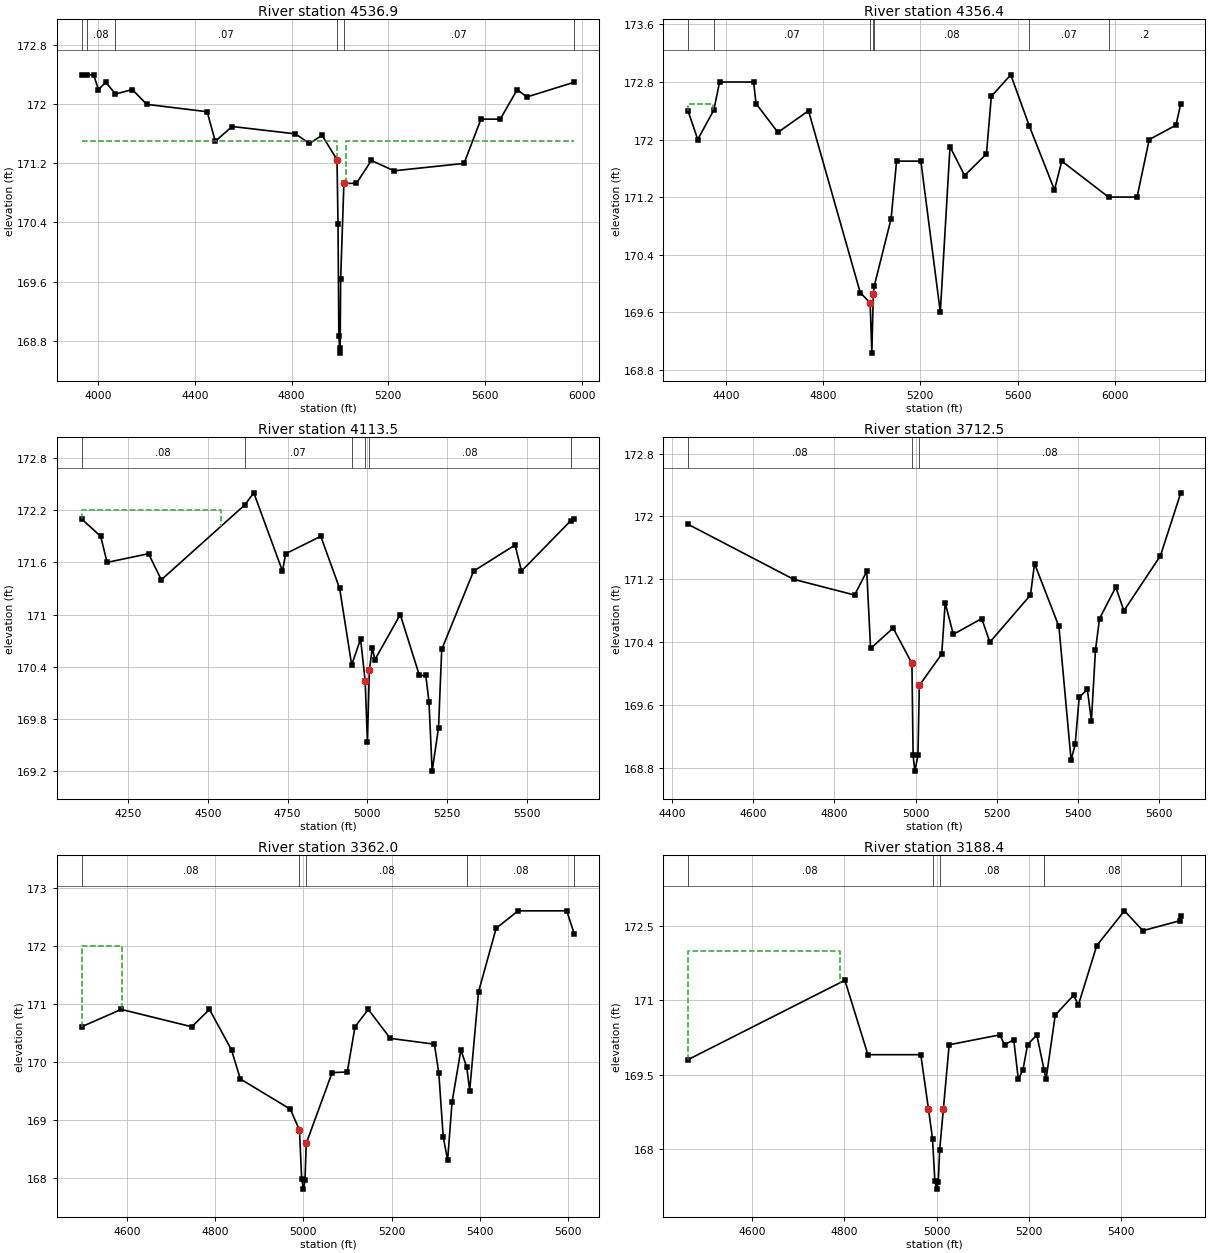
Type RM Length L Ch R = 1 ,4536.9  ,180.5,180.5,180.5
BEGIN DESCRIPTION:
Downstream Section of Bridge/Culvert/Weir
END DESCRIPTION:
XS GIS Cut Line= 4
    3042941.2198   13968049.3681     3043399.492   13968377.1833
    3043587.8132   13968862.3498    3043934.6041   13969753.1888
#Sta/Elev= 30
  3930.4   172.4  3953.1   172.4  3980.4   172.4  4000.4   172.2  4030.4   172.3
  4070.9  172.14  4140.4   172.2  4200.4     172  4450.4   171.9  4483.8   171.5
  4553.8   171.7  4815.9   171.6  4873.6  171.47    4926  171.58  4987.9  171.25
    4992  170.38  4995.5  168.86  4999.7  168.63  5000.8   168.7    5003  169.64
  5016.4  170.93  5068.2  170.93  5130.2  171.24  5223.8   171.1  5513.8   171.2
  5583.8   171.8  5663.8   171.8  5733.8   172.2  5773.8   172.1  5970.2   172.3
#Mann= 6 ,-1 , 0
  3930.4      .2       0  3953.1     .08       0  4070.9     .07       0
  4987.9     .07       0  5016.4     .07       0  5970.2      .2       0
#XS Ineff= 2 , 0
       0 4987.23   171.5 5023.07       0   171.5
Permanent Ineff=
       F       F
Bank Sta=4987.9,5016.4
XS Rating Curve= 0
Exp/Cntr=.5,.3

Type RM Length L Ch R = 1 ,4356.4  ,238.6,242.9,313.35
BEGIN DESCRIPTION:
Cross Section XS15
END DESCRIPTION:
XS GIS Cut Line= 4
     3042982.998   13968217.3152    3043330.9134   13968463.0904
    3043473.3864   13968844.6788    3043893.3716   13969963.4987
#Sta/Elev= 30
  4243.7   172.4  4283.7     172  4349.8  172.41  4373.7   172.8  4513.7   172.8
  4523.7   172.5  4613.7   172.1  4739.7   172.4  4952.7  169.87  4993.3  169.73
  5000.4  169.03  5006.4  169.85  5010.9  169.97  5079.7   170.9  5102.2   171.7
  5202.2   171.7  5282.2   169.6  5322.2   171.9  5382.2   171.5  5472.2   171.8
  5492.2   172.6  5572.2   172.9  5648.4  172.19  5752.2   171.3  5782.2   171.7
  5974.6   171.2  6092.2   171.2  6142.2     172  6252.2   172.2  6272.1   172.5
#Mann= 7 ,-1 , 0
  4243.7     .08       0  4349.8     .07       0  4993.3     .07       0
  5006.4     .07       0  5010.9     .08       0  5648.4     .07       0
  5974.6      .2       0
#XS Ineff= 2 , 0
       0    4345   172.5               0
Permanent Ineff=
       F       F
Bank Sta=4993.3,5006.4
XS Rating Curve= 0
Exp/Cntr=.3,.1

Type RM Length L Ch R = 1 ,4113.5  ,295.62,401,386.44
BEGIN DESCRIPTION:
Cross Section XS14
END DESCRIPTION:
XS GIS Cut Line= 3
    3042803.9315   13968031.3551    3043190.4705   13968708.8655
    3043327.7215   13969462.1504
#Sta/Elev= 30
  4104.1   172.1  4164.1   171.9  4184.1   171.6  4314.1   171.7  4354.1   171.4
  4615.6  172.26  4644.1   172.4  4734.1   171.5  4744.1   171.7  4854.1   171.9
  4913.3   171.3    4951  170.42  4978.9  170.72  4993.2  170.24  5000.4  169.54
  5006.4  170.36  5015.9  170.62  5023.6  170.48  5103.3     171  5163.3   170.3
  5183.3   170.3  5193.3     170  5203.3   169.2  5223.3   169.7  5233.3   170.6
  5333.3   171.5  5463.3   171.8  5483.3   171.5  5638.1  172.08    5649   172.1
#Mann= 6 ,-1 , 0
  4104.1     .08       0  4615.6     .07       0    4951     .08       0
  4993.2     .07       0  5006.4     .08       0  5638.1      .2       0
#XS Ineff= 2 , 0
       0    4540   172.2               0
Permanent Ineff=
       F       F
Bank Sta=4993.2,5006.4
XS Rating Curve= 0
Exp/Cntr=.3,.1

Type RM Length L Ch R = 1 ,3712.5  ,374.74,350.5,269.57
BEGIN DESCRIPTION:
Cross Section XS13
END DESCRIPTION:
XS GIS Cut Line= 3
    3042737.6481   13968091.8373    3042848.7521   13968581.0291
    3043026.8122   13969269.7889
#Sta/Elev= 30
  4439.9   171.9  4699.9   171.2  4849.9     171  4879.9   171.3  4889.3  170.32
  4944.8  170.58  4991.1  170.13    4994  168.96  4998.3  168.76  5005.9  168.96
  5009.3  169.85  5064.5  170.25  5072.9   170.9  5092.9   170.5  5162.9   170.7
  5182.9   170.4  5282.9     171  5292.9   171.4  5352.9   170.6  5382.9   168.9
  5392.9   169.1  5402.9   169.7  5422.9   169.8  5432.9   169.4  5442.9   170.3
  5452.9   170.7  5492.9   171.1  5512.9   170.8  5602.9   171.5  5652.9   172.3
#Mann= 3 ,-1 , 0
  4439.9     .08       0  4991.1     .07       0  5009.3     .08       0
Bank Sta=4991.1,5009.3
XS Rating Curve= 0
Exp/Cntr=.3,.1

Type RM Length L Ch R = 1 ,3362.0  ,181.33,173.6,130.62
BEGIN DESCRIPTION:
Cross Section XS12
Ineffective flow beyond Drainage Area Divide
END DESCRIPTION:
XS GIS Cut Line= 2
    3042274.3995    13968306.688    3042890.4333   13969238.7184
#Sta/Elev= 30
  4497.2   170.6  4587.2   170.9  4747.2   170.6  4787.2   170.9  4837.2   170.2
  4857.2   169.7  4970.4  169.18  4991.2  168.82  4996.3  167.97  5000.4   167.8
  5003.7  167.95  5006.7  168.59  5065.3  169.81  5099.6  169.82  5117.2   170.6
  5147.2   170.9  5197.2   170.4  5297.2   170.3  5307.2   169.8  5317.2   168.7
  5327.2   168.3  5337.2   169.3  5357.2   170.2  5370.6   169.9  5377.2   169.5
  5397.2   171.2  5437.2   172.3  5487.2   172.6  5597.2   172.6  5614.4   172.2
#Mann= 5 ,-1 , 0
  4497.2     .08       0  4991.2     .07       0  5006.7     .08       0
  5370.6     .08       0  5614.4      .2       0
#XS Ineff= 2 , 0
       0    4590     172               0
Permanent Ineff=
       F       F
Bank Sta=4991.2,5006.7
XS Rating Curve= 0
Exp/Cntr=.3,.1

Type RM Length L Ch R = 1 ,3188.4  ,170.2,160.4,147.9
BEGIN DESCRIPTION:
Cross Section XS11
Ineffective flow beyond Drainage Area Divide
END DESCRIPTION:
XS GIS Cut Line= 4
      3042058.93     13968509.32      3042430.84     13968850.39
      3042489.54     13968868.78      3042810.64     13969254.68
#Sta/Elev= 29
  4461.2   169.8  4801.2   171.4  4851.2   169.9  4965.8   169.9 4982.37  168.81
  4991.2  168.21  4996.3  167.36  5000.4  167.19  5003.7  167.34  5006.7  167.98
 5014.81  168.81  5027.3   170.1  5137.3   170.3  5147.3   170.1  5167.3   170.2
  5177.3   169.4  5187.3   169.6  5197.3   170.1  5217.3   170.3  5232.9   169.6
  5237.3   169.4  5257.3   170.7  5297.3   171.1  5307.3   170.9  5347.3   172.1
  5407.3   172.8  5447.3   172.4  5527.3   172.6  5529.4   172.7
#Mann= 5 ,-1 , 0
  4461.2     .08       0  4991.2     .07       0  5006.7     .08       0
  5232.9     .08       0  5529.4      .2       0
#XS Ineff= 2 , 0
       0    4790     172               0
Permanent Ineff=
       F       F
Bank Sta=4982.37,5014.81
XS Rating Curve= 0
Exp/Cntr=.3,.1

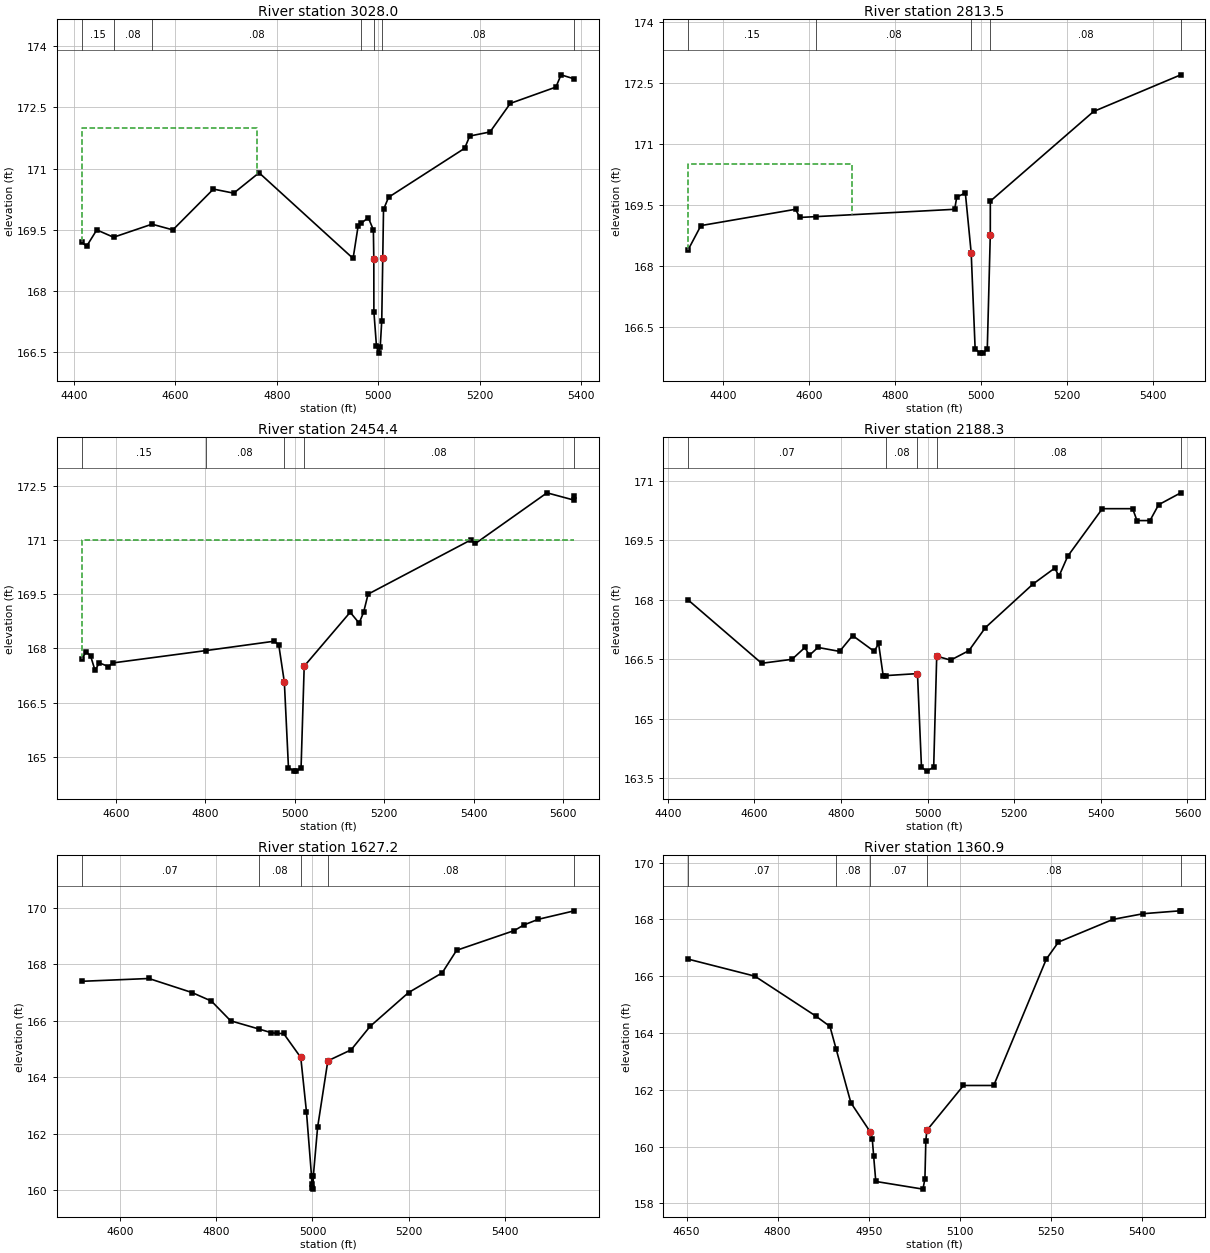
Type RM Length L Ch R = 1 ,3028.0  ,137.3,214.5,227.9
BEGIN DESCRIPTION:
Cross Section XS10
Ineffective flow beyond Drainage Area Divide
END DESCRIPTION:
XS GIS Cut Line= 3
    3041952.0191    13968696.098    3042376.5398   13968951.4488
    3042711.6877   13969289.7886
#Sta/Elev= 30
  4414.8   169.2  4424.8   169.1  4444.8   169.5  4477.9  169.32  4553.7  169.64
  4594.8   169.5  4674.8   170.5  4714.8   170.4  4764.8   170.9  4950.2   168.8
  4960.2   169.6  4965.9  169.66  4980.2   169.8  4990.2   169.5 4991.07  168.78
  4991.2   167.5  4996.3  166.65  5000.4  166.48  5003.7  166.63  5006.7  167.27
  5008.7   168.8  5010.2     170  5020.2   170.3  5170.2   171.5  5180.2   171.8
  5220.2   171.9  5260.2   172.6  5350.2     173  5360.2   173.3  5386.4   173.2
#Mann= 7 ,-1 , 0
  4414.8     .15       0  4477.9     .08       0  4553.7     .08       0
  4965.9     .08       0  4991.2     .07       0  5006.7     .08       0
  5386.4      .2       0
#XS Ineff= 2 , 0
       0    4760     172               0
Permanent Ineff=
       F       F
Bank Sta=4991.07,5008.7
XS Rating Curve= 0
Exp/Cntr=.3,.1

Type RM Length L Ch R = 1 ,2813.5  ,384.8,359.1,333.72
BEGIN DESCRIPTION:
Cross Section XS09
Xsec extended to Drainage Area Divide.  Ineffective flow beyond limits of xsec
END DESCRIPTION:
XS GIS Cut Line= 4
       3041636.2     13968748.66      3042225.24     13968956.88
      3042227.01     13969035.01      3042593.59      13969283.4
#Sta/Elev= 17
  4318.3   168.4  4348.3     169  4568.3   169.4  4578.3   169.2  4615.8  169.22
  4938.3   169.4  4943.1   169.7  4963.1   169.8  4976.7  168.33  4985.9  165.97
    4998  165.87  5003.6  165.87  5014.1  165.97  5021.1  168.77  5021.2   169.6
  5261.2   171.8    5464   172.7
#Mann= 5 ,-1 , 0
  4318.3     .15       0  4615.8     .08       0  4976.7     .07       0
  5021.1     .08       0    5464      .2       0
#XS Ineff= 2 , 0
       0    4700   170.5               0
Permanent Ineff=
       F       F
Bank Sta=4976.7,5021.1
XS Rating Curve= 0
Exp/Cntr=.3,.1

Type RM Length L Ch R = 1 ,2454.4  ,252.71,266.1,243.97
BEGIN DESCRIPTION:
Cross Section XS08
Xsec extended to Drainage Area Divide.  Ineffective flow beyond limits of xsec
END DESCRIPTION:
XS GIS Cut Line= 4
    3041490.6094   13968979.4146      3041901.47     13969109.28
      3041934.13     13969159.26    3042497.8315   13969395.1208
#Sta/Elev= 25
  4523.3   167.7  4533.3   167.9  4543.3   167.8  4553.3   167.4  4563.3   167.6
  4583.3   167.5  4593.3   167.6  4800.8  167.94  4954.2   168.2  4964.2   168.1
  4976.7  167.07  4985.9  164.71    4998  164.61  5003.6  164.61  5014.1  164.71
  5021.1  167.51  5123.9     169  5143.9   168.7  5153.9     169  5163.9   169.5
  5393.9     171  5403.9   170.9  5563.9   172.3  5623.9   172.1    5625   172.2
#Mann= 5 ,-1 , 0
  4523.3     .15       0  4800.8     .08       0  4976.7     .07       0
  5021.1     .08       0    5625      .2       0
#XS Ineff= 2 , 0
       0  4523.3     171               0
Permanent Ineff=
       F       F
Bank Sta=4976.7,5021.1
XS Rating Curve= 0
Exp/Cntr=.3,.1

Type RM Length L Ch R = 1 ,2188.3  ,602.7,561.1,521.7
BEGIN DESCRIPTION:
Cross Section XS07
END DESCRIPTION:
XS GIS Cut Line= 3
    3041215.1655   13969134.8404     3041691.149   13969308.7228
      3042283.02   13969527.3115
#Sta/Elev= 30
  4446.9     168  4616.9   166.4  4686.9   166.5  4716.9   166.8  4726.9   166.6
  4746.9   166.8  4796.9   166.7  4826.9   167.1  4876.9   166.7  4886.9   166.9
  4897.7  166.07  4904.2  166.09  4976.7  166.14  4985.9  163.78    4998  163.68
  5014.1  163.78  5021.1  166.58  5053.3  166.48  5095.5  166.72  5133.5   167.3
  5243.5   168.4  5293.5   168.8  5303.5   168.6  5323.5   169.1  5403.5   170.3
  5473.5   170.3  5483.5     170  5513.5     170  5533.5   170.4  5584.6   170.7
#Mann= 5 ,-1 , 0
  4446.9     .07       0  4904.2     .08       0  4976.7     .07       0
  5021.1     .08       0  5584.6      .2       0
Bank Sta=4976.7,5021.1
XS Rating Curve= 0
Exp/Cntr=.3,.1

Type RM Length L Ch R = 1 ,1627.2  ,265.93,266.3,267.77
BEGIN DESCRIPTION:
Cross Section XS06
END DESCRIPTION:
XS GIS Cut Line= 2
    3041274.9832   13969839.6252    3042298.2548   13969783.7642
#Sta/Elev= 27
  4519.8   167.4  4659.8   167.5  4749.8     167  4789.8   166.7  4829.8     166
  4888.4  165.71  4913.9  165.58    4927  165.55    4940  165.55  4975.7   164.7
  4987.5  162.78  4998.1  160.49  4998.7  160.22  4999.6  160.08  5001.1  160.03
  5001.9  160.51  5010.7  162.22    5032  164.58  5080.4  164.97  5119.8   165.8
  5199.8     167  5269.8   167.7  5299.8   168.5  5419.8   169.2  5439.8   169.4
  5469.8   169.6  5544.6   169.9
#Mann= 5 ,-1 , 0
  4519.8     .07       0  4888.4     .08       0  4975.7     .07       0
    5032     .08       0  5544.6      .2       0
Bank Sta=4975.7,5032
XS Rating Curve= 0
Exp/Cntr=.3,.1

Type RM Length L Ch R = 1 ,1360.9  ,227.43,231.7,230.46
BEGIN DESCRIPTION:
Cross Section XS05
END DESCRIPTION:
XS GIS Cut Line= 2
    3041434.9487    13970098.617     3042244.933   13970050.3734
#Sta/Elev= 22
  4652.5   166.6  4762.5     166  4862.5   164.6  4886.2  164.23  4896.3  163.44
  4920.7  161.54  4952.7  160.51  4955.9  160.27  4958.1  159.68  4961.7  158.77
  5039.4   158.5  5042.6  158.87  5044.1  160.21  5045.8  160.57  5106.1  162.15
  5155.9  162.15  5242.5   166.6  5262.5   167.2  5352.5     168  5402.5   168.2
  5462.5   168.3  5463.9   168.3
#Mann= 5 ,-1 , 0
  4652.5     .07       0  4896.3     .08       0  4952.7     .07       0
  5045.8     .08       0  5463.9      .2       0
Bank Sta=4952.7,5045.8
XS Rating Curve= 0
Exp/Cntr=.3,.1

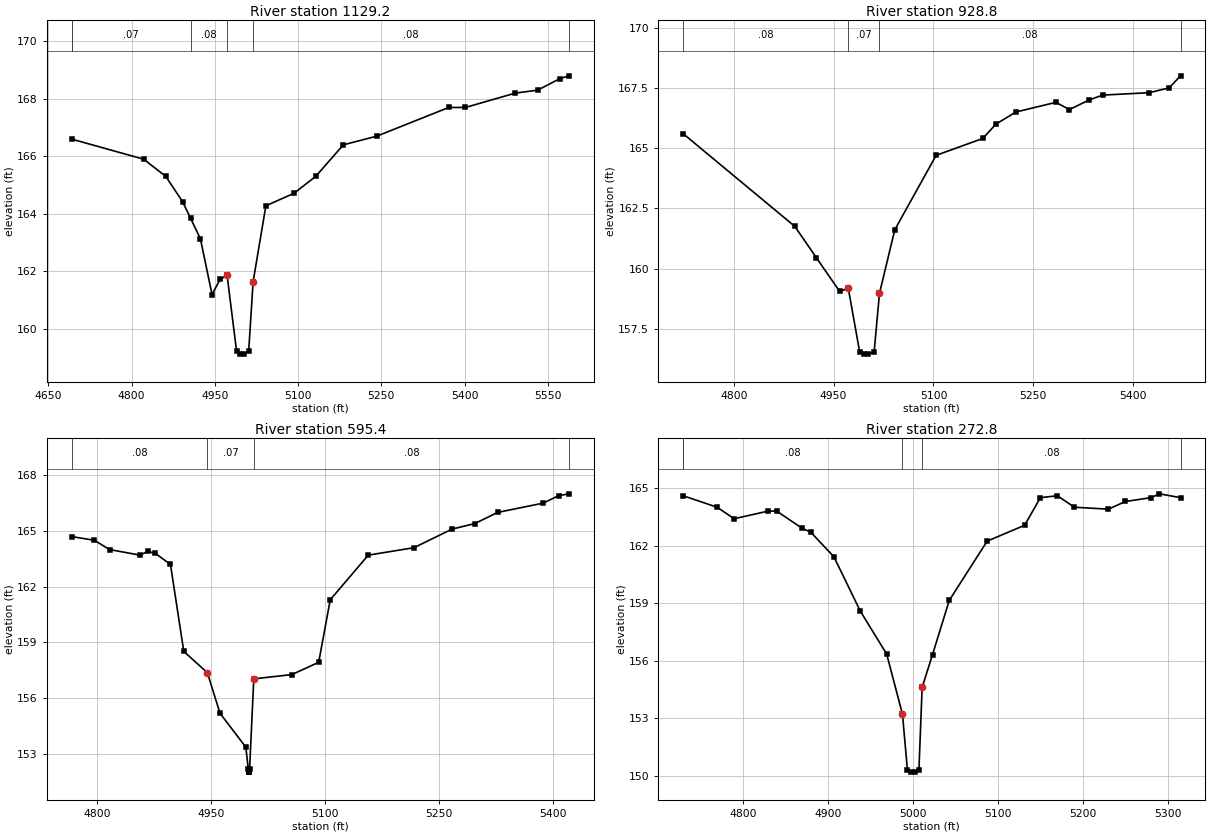
Type RM Length L Ch R = 1 ,1129.2  ,190.95,200.4,195.7
BEGIN DESCRIPTION:
Cross Section XS04
END DESCRIPTION:
XS GIS Cut Line= 2
    3041493.3488   13970311.9044    3042389.6637   13970289.0522
#Sta/Elev= 25
  4691.6   166.6  4821.6   165.9  4861.6   165.3  4891.8  164.42  4906.3  163.84
  4923.9  163.13  4944.9  161.19  4959.2  161.72    4972  161.86  4989.1  159.22
  4996.1  159.12  5002.3  159.12  5010.9  159.22  5018.9  161.64  5041.9  164.28
  5092.2  164.71  5131.6   165.3  5181.6   166.4  5241.6   166.7  5371.6   167.7
  5401.6   167.7  5491.6   168.2  5531.6   168.3  5571.6   168.7  5588.2   168.8
#Mann= 6 , 1 , 0
  4691.6      .2       0  4691.6     .07       0  4906.3     .08       0
    4972     .07       0  5018.9     .08       0  5588.2      .2       0
Bank Sta=4972,5018.9
XS Rating Curve= 0
Exp/Cntr=.3,.1

Type RM Length L Ch R = 1 ,928.8   ,284.08,333.4,290.65
BEGIN DESCRIPTION:
Cross Section XS03
END DESCRIPTION:
XS GIS Cut Line= 2
    3041594.2795    13970492.183    3042340.7853   13970461.7134
#Sta/Elev= 22
    4724   165.6  4891.8  161.75  4923.9  160.46  4959.2  159.05    4972  159.19
  4989.1  156.55  4996.1  156.45  5002.3  156.45  5010.9  156.55  5018.9  158.97
  5041.9  161.61    5104   164.7    5174   165.4    5194     166    5224   166.5
    5284   166.9    5304   166.6    5334     167    5354   167.2    5424   167.3
    5454   167.5  5471.1     168
#Mann= 4 ,-1 , 0
    4724     .08       0    4972     .07       0  5018.9     .08       0
  5471.1      .2       0
Bank Sta=4972,5018.9
XS Rating Curve= 0
Exp/Cntr=.3,.1

Type RM Length L Ch R = 1 ,595.4   ,301.11,322.6,316.48
BEGIN DESCRIPTION:
Cross Section XS02
END DESCRIPTION:
XS GIS Cut Line= 2
    3041612.0534   13970695.3139     3042250.646   13970834.9663
#Sta/Elev= 28
  4766.9   164.7  4796.9   164.5  4816.9     164  4856.9   163.7  4866.9   163.9
  4876.9   163.8  4896.9   163.2  4914.4  158.52  4945.4  157.37    4962  155.19
    4996  153.36  4999.1  152.21  4999.6  152.04  4999.9  152.03    5000  152.02
  5000.9  152.18  5006.4  157.04  5056.4  157.27  5091.7  157.93  5106.9   161.3
  5156.9   163.7  5216.9   164.1  5266.9   165.1  5296.9   165.4  5326.9     166
  5386.9   166.5  5406.9   166.9  5420.6     167
#Mann= 4 ,-1 , 0
  4766.9     .08       0  4945.4     .07       0  5006.4     .08       0
  5420.6      .2       0
Bank Sta=4945.4,5006.4
XS Rating Curve= 0
Exp/Cntr=.3,.1

Type RM Length L Ch R = 1 ,272.8   ,0,0,0
BEGIN DESCRIPTION:
Cross Section XS01
END DESCRIPTION:
XS GIS Cut Line= 2
    3041584.1229   13970875.5925    3042051.3239   13971227.2627
#Sta/Elev= 28
  4729.6   164.6  4769.6     164  4789.6   163.4  4829.6   163.8  4839.6   163.8
  4869.6   162.9  4879.6   162.7  4906.8  161.42  4937.9  158.58  4968.9  156.34
  4987.5   153.2  4993.3  150.28    4997  150.18  5002.3  150.18  5006.8  150.28
  5010.6   154.6  5022.8  156.31  5042.5  159.14    5087  162.23  5131.1  163.06
  5149.6   164.5  5169.6   164.6  5189.6     164  5229.6   163.9  5249.6   164.3
  5279.6   164.5  5289.6   164.7  5314.4   164.5
#Mann= 5 , 1 , 0
  4729.6      .2       0  4729.6     .08       0  4987.5     .07       0
  5010.6     .08       0  5314.4      .2       0
Bank Sta=4987.5,5010.6
XS Rating Curve= 0
Exp/Cntr=.3,.1

Chan Stop Cuts=-1